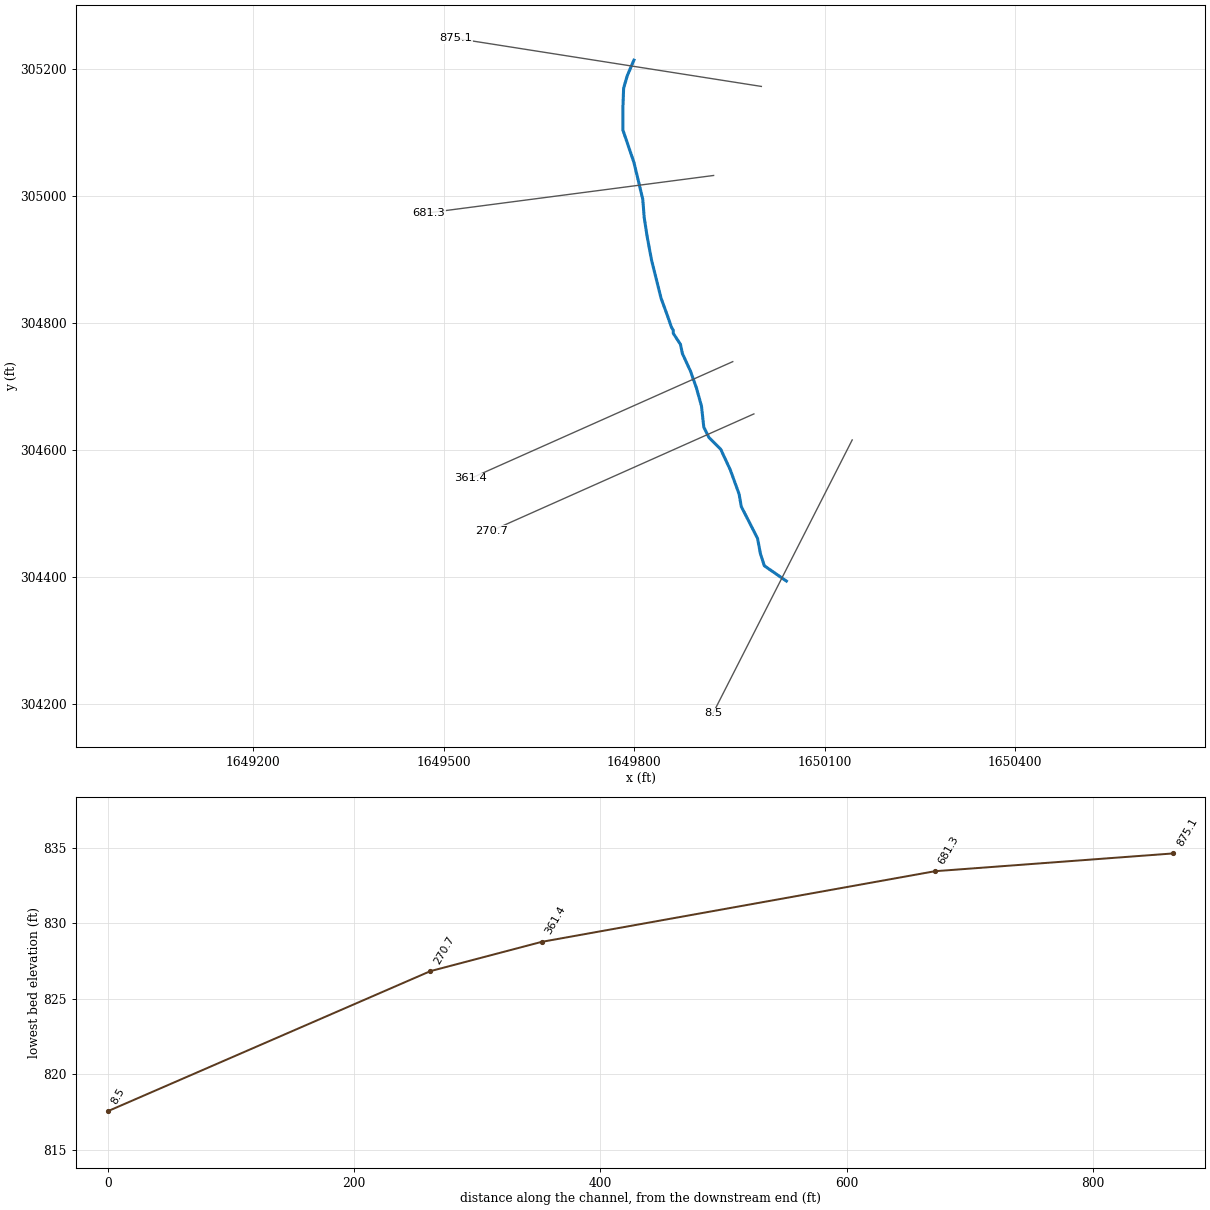
--- CABINBRNCH.prj (project) ---

Proj Title=CABINBRNCH
Current Plan=p01
Default Exp/Contr=0,0
English Units
Geom File=g01
Flow File=f01
Plan File=p01
BEGIN DESCRIPTION:
END DESCRIPTION:
DSS Export Rating Curves= 0
DSS Export Rating Curve Sorted= 0
DSS Export Volume Flow Curves= 0
DXF OffsetX= 0
DXF OffsetY= 0
DXF ScaleX= 0
DXF ScaleY= 0

--- CABINBRNCH.p01 (plan) ---

Plan Title=Floodplain
Program Version=4.00
Geom File=g01
Flow File=f01
K Sum by GR=0
Std Step Tol=0.01
Critical Tol=0.01
Num of Std Step Trials=20
Max Error Tol=0.3
Flow Tol Ratio=0.001
Split Flow NTrial=30
Split Flow Tol=0.02
Split Flow Ratio=0.02
Log Output Level=0
Friction Slope Method=1
Unsteady Friction Slope Method=2
Unsteady Bridges Friction Slope Method=1
Global Log Level=0
CheckData=False
Run HTab=0
Run UNet=0
Run PostProcess=0
UNET Theta=0
UNET Theta Warmup=0
UNET ZTol=0
UNET ZSATol=0
UNET MxIter=0
UNET MaxInSteps=0
UNET DtIC=0
UNET DtMin=0
UNET MaxCRTS=0
UNET WFStab=0
UNET SFStab=0
UNET WFX=0
UNET SFX=0
UNET DSS MLevel=0
UNET DZMax Abort=0
UNET Convert EG Bridges=0
UNET Use Existing IB Tables=0
UNET Froude Limit=0
UNET Froude Power=0
Write IC File=0
Echo Input=False
Echo Output=False
Write Detailed=0

--- CABINBRNCH.f01 (steady flow) ---

Flow Title=NFF Regression Equation
Program Version=4.10
Number of Profiles= 1
Profile Names=P100yr
River Rch & RM=CABINBRNCH,Main            ,875.1
993.5687
River Rch & RM=CABINBRNCH,Main            ,270.7
996.4043
River Rch & RM=CABINBRNCH,Main            ,8.5
1915.483
Boundary for River Rch & Prof#=CABINBRNCH,Main            , 1
Up Type= 0
Dn Type= 1
Dn Known WS=827.31
DSS Import GetInterval= 0
DSS Import GetPeak= 0
DSS Import FillOption= 0

--- CABINBRNCH.g01 (geometry) ---

Geom Title=USGS 10m DEM
Program Version=4.10

River Reach=CABINBRNCH      ,Main
Reach XY= 30
     1649799.729      305214.149     1649789.306      305189.827
     1649783.515      305170.138     1649782.356      305138.866
     1649782.356       305104.12     1649799.729      305053.159
     1649813.628      304995.249     1649815.944      304966.294
     1649820.577      304936.181     1649827.526      304899.118
     1649842.583      304838.892      1649850.69      304816.886
     1649858.798      304793.722     1649861.768      304788.524
     1649861.624      304784.059     1649873.014      304766.595
     1649876.051      304752.168     1649888.959      304724.073
     1649898.071      304698.256     1649906.095      304669.496
     1649909.759      304636.206     1649917.866      304619.991
     1649936.398       304601.46     1649951.454       304569.03
     1649965.352       304530.81     1649968.827       304511.12
     1649994.307      304461.318      1649998.94      304436.995
     1650005.068      304417.967     1650039.784      304393.933

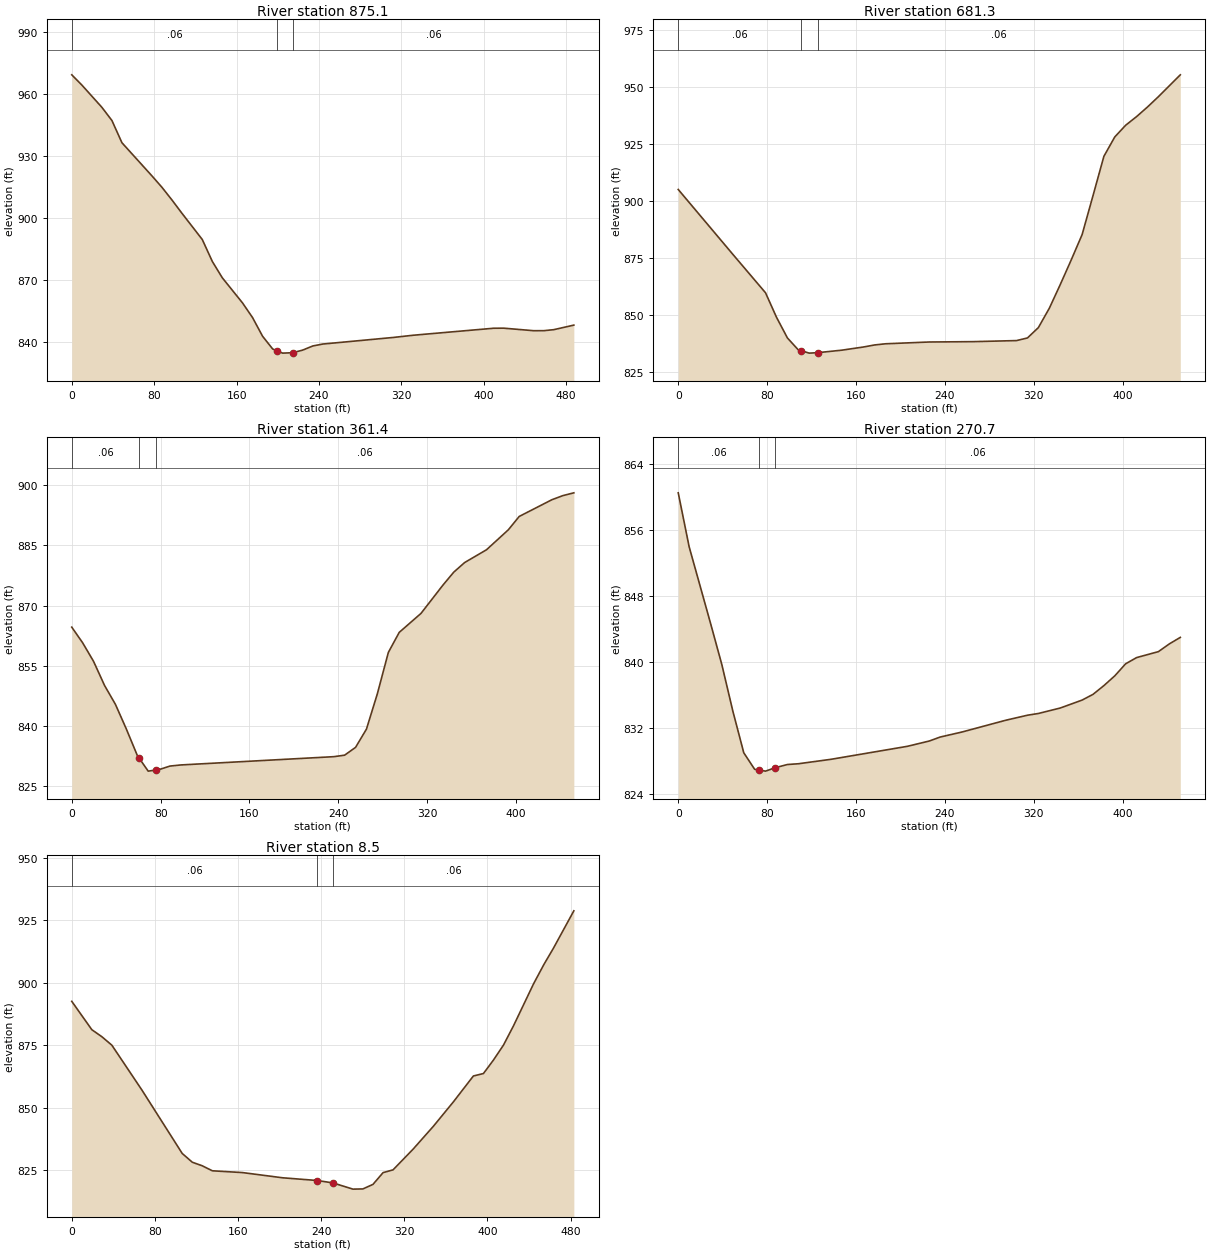
Type RM Length L Ch R = 1 ,875.1   ,187.2,193.7,200.2
XS GIS Cut Line= 2
     1650000.401      305172.775     1649518.925      305248.506
#Sta/Elev= 30
       0  969.41     9.8  964.46    29.2  953.69      39  947.27    48.7  936.52
      78  920.37    87.7  914.84    97.5  908.64   107.2   902.2   126.7  889.65
   136.5  878.97   146.2  871.06   165.7  858.98   175.5  851.84   185.2  842.82
     195  836.64   199.6  835.68   204.7  834.62   214.6  834.82   224.2  836.09
     234  838.09   243.7  839.02   311.9   842.2   331.4  843.28   409.4  846.67
   419.2  846.71   448.4  845.48   458.2  845.49   467.9  845.98   487.4  848.19
#Mann= 3 , 0 , 0
       0     .06       0   199.6    .045       0   214.6     .06       0
Bank Sta=199.6,214.6
XS Rating Curve= 0 ,0
Exp/Cntr=0.3,0.1

Type RM Length L Ch R = 1 ,681.3   ,312.9,319.4,325.8
XS GIS Cut Line= 2
     1649925.206      305032.564     1649477.048      304973.884
#Sta/Elev= 30
       0   905.2    49.1   876.8    78.6  859.89    88.4  849.24    98.3  840.09
   108.1  834.86   110.4  834.53   117.9  833.44   125.4  833.63   147.4  834.74
     167  836.15   176.9  837.03   186.7  837.54     226  838.32   265.3  838.47
   304.6  838.94   314.4   840.1   324.2  844.62   334.1  853.14   343.9  863.48
   353.7   874.2   363.6  885.42   373.4  902.48   383.2  919.74     393  928.24
   402.8  933.37   412.7  937.19   422.5  941.39   432.3  945.91     452  955.48
#Mann= 3 , 0 , 0
       0     .06       0   110.4    .045       0   125.4     .06       0
Bank Sta=110.4,125.4
XS Rating Curve= 0 ,0
Exp/Cntr=0.3,0.1

Type RM Length L Ch R = 1 ,361.4   ,90.4,90.4,90.5
XS GIS Cut Line= 2
     1649955.347      304739.416     1649542.491      304555.464
#Sta/Elev= 30
       0  864.63     9.8  860.73    19.6  856.12    29.5  850.11    39.3   845.4
    49.1  839.28      59  832.66    60.4   832.1    68.8  828.76    75.4  829.02
    78.6  829.14    88.4  830.02    98.3   830.3   235.8  832.36   245.6  832.73
   255.5  834.68   265.3  839.23   275.1  848.02     285  858.33   294.8  863.33
   314.4  868.06   334.1  875.09   343.9  878.34   353.7  880.73   373.4  883.92
     393  888.88   402.8  892.21   432.3  896.39   442.2  897.41     452   898.1
#Mann= 3 , 0 , 0
       0     .06       0    60.4    .045       0    75.4     .06       0
Bank Sta=60.4,75.4
XS Rating Curve= 0 ,0
Exp/Cntr=0.3,0.1

Type RM Length L Ch R = 1 ,270.7   ,245.9,262,278
XS GIS Cut Line= 2
     1649988.654      304657.128     1649575.798      304473.175
#Sta/Elev= 30
       0  860.47     9.8  853.96    29.5  844.49    39.3  839.68    49.1  834.11
      59  829.04    68.8  827.04    72.5  826.96    78.6  826.82    87.5  827.24
    98.3  827.62   108.1  827.71   137.6  828.25   206.3  829.82     226  830.46
   235.8  830.94   255.5  831.55   294.8  832.97   314.4  833.58   324.2  833.79
   343.9  834.45   363.6  835.41   373.4   836.1   383.2  837.16     393  838.34
   402.8   839.8   412.7  840.55   432.3  841.27   442.2  842.21     452  842.99
#Mann= 3 , 0 , 0
       0     .06       0    72.5    .045       0    87.5     .06       0
Bank Sta=72.5,87.5
XS Rating Curve= 0 ,0
Exp/Cntr=0.3,0.1

Type RM Length L Ch R = 1 ,8.5     ,11.6,8.5,5.5
XS GIS Cut Line= 2
     1650143.448      304616.126     1649924.195      304185.558
#Sta/Elev= 30
       0  892.55    19.3  881.23      29  878.41    38.6  875.03    67.6  857.06
   106.3  831.79     116  828.29   125.6  826.86   135.3  824.86   164.3  824.15
   202.9  822.07   236.4  820.98   251.4  820.02   270.6  817.54   280.2  817.62
   289.9  819.44   299.6  824.13   309.2  825.24   328.6  833.55   347.9  842.59
   367.2  852.36   386.5  862.73   396.2  863.72   405.9  869.14   415.5  875.09
   425.2  882.84   444.5  899.61   454.2  907.14   463.8  913.96   483.2  928.71
#Mann= 3 , 0 , 0
       0     .06       0   236.4    .045       0   251.4     .06       0
Bank Sta=236.4,251.4
XS Rating Curve= 0 ,0
Exp/Cntr=0.3,0.1

Chan Stop Cuts=-1
Use User Specified Reach Order=0
Composite Channel Slope=5